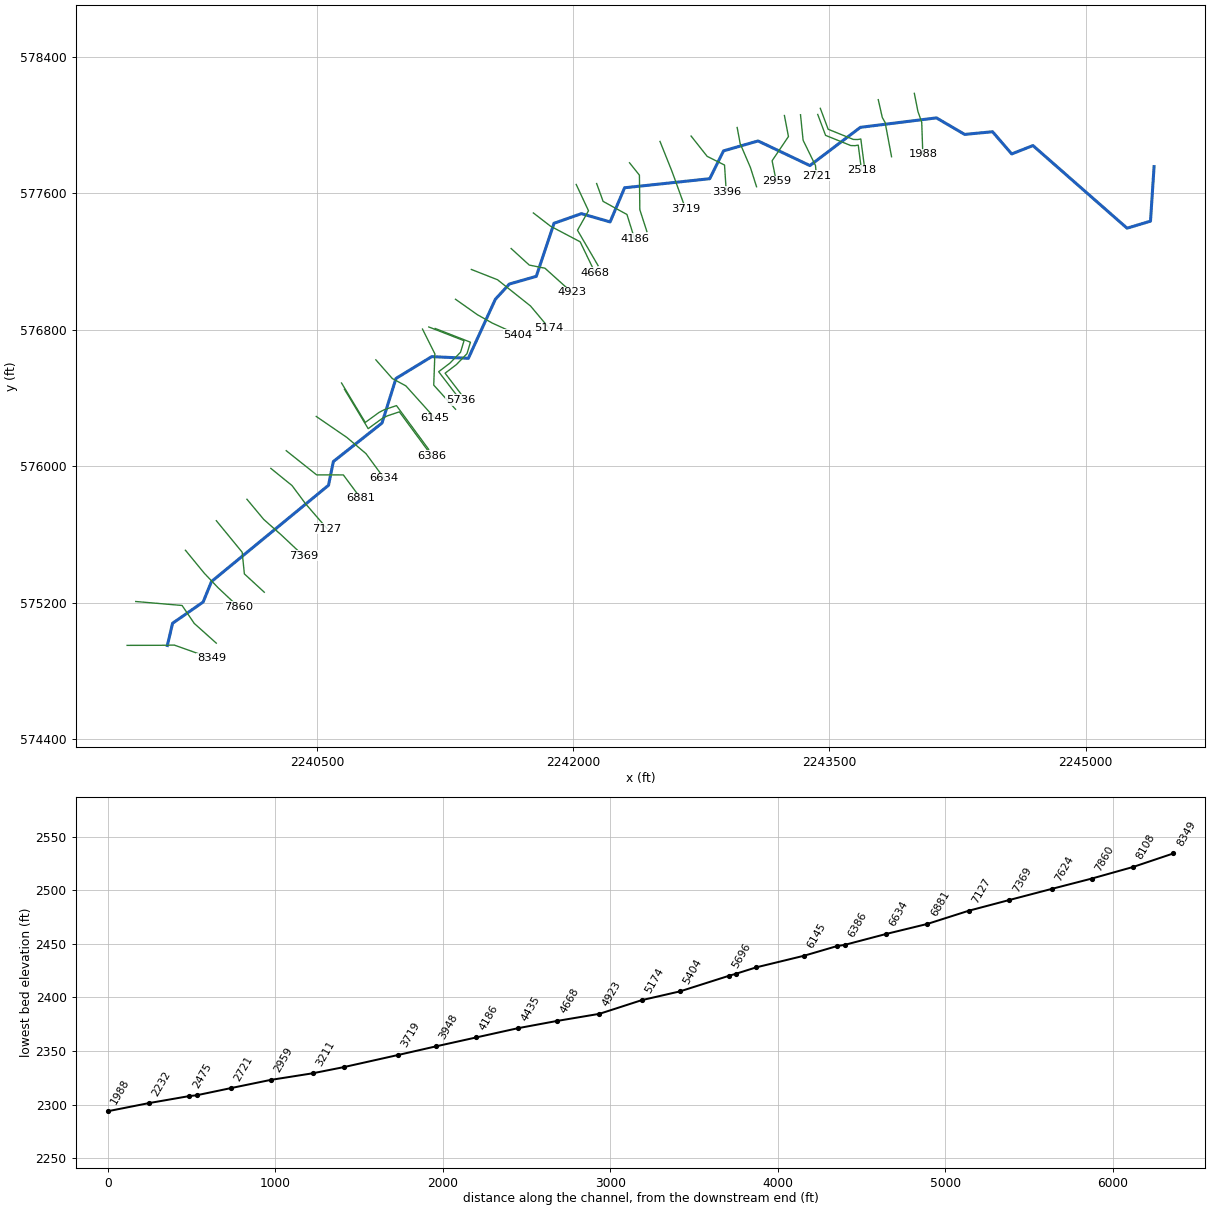
--- HAMILTRN.prj (project) ---

Proj Title=HAMILTRN
Current Plan=p01
Default Exp/Contr=0,0
English Units
Geom File=g01
Flow File=f01
Plan File=p01
BEGIN DESCRIPTION:
----------MODEL BY WOOD PLC 2022----------
AFH study
Randolph County, WV
HEC-RAS Version: RAS 6.2
Vertical Datum: NAVD88
Projection: NAD 1983 StatePlane West Virginia S FIPS 4702 (US Feet)
Terrain: 1-meter LIDAR (FEMA Region III 3DEP collected 2016-2018)
Land Use: 2019 NLCD
Hydrologic Method:
WV SIR2010-5033 regression equations
Additional Model Notes:
None
END DESCRIPTION:
DSS Export Rating Curves= 0
DSS Export Rating Curve Sorted= 0
DSS Export Volume Flow Curves= 0
DXF OffsetX= 0
DXF OffsetY= 0
DXF ScaleX= 0
DXF ScaleY= 0

--- HAMILTRN.p01 (plan) ---

Plan Title=Floodplain
Program Version=6.20
Short Identifier=Floodplain
Geom File=g01
Flow File=f01
Subcritical Flow
K Sum by GR= 0
Std Step Tol= 0.01
Critical Tol= 0.01
Num of Std Step Trials= 20
Max Error Tol= 0.3
Flow Tol Ratio= 0.001
Split Flow NTrial= 30
Split Flow Tol= 0.02
Split Flow Ratio= 0.02
Log Output Level= 0
Friction Slope Method= 1
Unsteady Friction Slope Method= 2
Unsteady Bridges Friction Slope Method= 1
Parabolic Critical Depth
Global Vel Dist= 0 , 0 , 0
Global Log Level= 0
CheckData=True
Encroach Param=-1 ,0,0, 0
Mapping Interval=1HOUR
Computation Time Step Use Courant=        0
Computation Time Step Use Time Series=    0
Computation Time Step Count To Double=0
Computation Time Step Max Doubling=0
Computation Time Step Max Halving=0
Computation Time Step Residence Courant=0
Run HTab= 0
Run UNet= 0
Run Sediment= 0
Run PostProcess= 0
Run WQNet= 0
Run RASMapper=-1
UNET Theta= 0
UNET Theta Warmup= 0
UNET ZTol= 0
UNET ZSATol= 0
UNET MxIter= 0
UNET Max Iter WO Improvement= 0
UNET MaxInSteps= 0
UNET DtIC= 0
UNET DtMin= 0
UNET MaxCRTS= 0
UNET WFStab= 0
UNET SFStab= 0
UNET WFX= 1
UNET SFX= 1
UNET Gravity=32.174
UNET 1D Methodology=Finite Difference
UNET DSS MLevel= 1
UNET Pardiso=0
UNET DZMax Abort= 0
UNET Use Existing IB Tables= 0
UNET Froude Reduction=False
UNET Froude Limit= 0
UNET Froude Power= 0
UNET D1 Cores= 0
UNET WindReference=Eulerian
UNET WindDragFormulation=Hsu (1988)
UNET D2 Coriolis=0
UNET D2 Cores= 0
UNET D2 Theta= 1
UNET D2 Theta Warmup= 1
UNET D2 Z Tol= 0.01
UNET D2 Volume Tol= 0.01
UNET D2 Max Iterations= 20
UNET D2 Equation= 0
UNET D2 RampUpFraction=0.1
UNET D2 TimeSlices= 1
UNET D2 Turbulence Formulation=Non-Conservative (original)
UNET D2 Eddy Viscosity=0.3
UNET D2 Transverse Eddy Viscosity=0.1
UNET D2 Smagorinsky Mixing=0
UNET D2 BCVolumeCheck=0
UNET D2 Cores=0
UNET D2 SolverType=PARDISO (Direct)
UNET D2 Minimum Iterations= 2147483647
UNET D2 Maximum Iterations= 2147483647
UNET D2 Restart Number= 10
UNET D2 Relaxation Coeff=1.3
UNET D2 SOR Precondition Iterations= 10
UNET D2 ILUT Maximum Fill= 8
UNET D2 ILUT Tolerance=1E-08
UNET D1D2 MaxIter= 0
UNET D1D2 ZTol=0.01
UNET D1D2 QTol=0.1
UNET D1D2 MinQTol=1
Write IC File= 0
Write IC File at Fixed DateTime=0
Write IC File at Sim End=0
Echo Input=False
Echo Parameters=False
Echo Output=False
Write Detailed= 0
HDF Write Warmup=0
HDF Write Time Slices=0
HDF Flush=0
HDF Compression= 1
HDF Chunk Size= 1
HDF Spatial Parts= 1
HDF Use Max Rows=0
HDF Fixed Rows= 1
Calibration Method= 0
Calibration Iterations= 20
Calibration Max Change=0.05
Calibration Tolerance=0.2
Calibration Maximum=1.5
Calibration Minimum=0.5
Calibration Optimization Method= 1
WQ AD Non Conservative
WQ ULTIMATE=-1
WQ Max Comp Step=1HOUR
WQ Output Interval=15MIN
WQ Output Selected Increments= 0
WQ Output face flow=0
WQ Output face velocity=0
WQ Output face area=0
WQ Output face dispersion=0
WQ Output cell volume=0
WQ Output cell surface area=0
WQ Output cell continuity=0
WQ Output cumulative cell continuity=0
WQ Output face conc=0
WQ Output face dconc_dx=0
WQ Output face courant=0
WQ Output face peclet=0
WQ Output face adv mass=0
WQ Output face disp mass=0
WQ Output cell mass=0
WQ Output cell source sink temp=0
WQ Output nsm pathways=0
WQ Output nsm derived pathways=0
WQ Create Restart=0
WQ Fixed Restart=0
WQ System Summary=0
WQ Write To DSS=0
Sorting and Armoring Iterations= 10
XS Update Threshold= 0.02
Bed Roughness Predictor= 0
Hydraulics Update Threshold= 0.02
Energy Slope Method= 1
Volume Change Method= 1
Sediment Retention Method= 0
Sediment TS Multiplier= 1
Warm Up Method= 0
XS Weighting Method= 0
Number of US Weighted Cross Sections= 1
Number of DS Weighted Cross Sections= 1
Upstream XS Weight=0
Main XS Weight=1
Downstream XS Weight=0
Number of DS XS's Weighted with US Boundary= 1
Upstream Boundary Weight= 1
Weight of XSs Associated with US Boundary= 0
Number of US XS's Weighted with DS Boundary= 1
Downstream Boundary Weight= 0.5
Weight of XSs Associated with DS Boundary= 0.5
Percentile Method= 0
Sediment Output Level= 3
Mass or Volume Output= 0
Output Increment Type= 1
Profile and TS Output Increment= 1
Transport Output Increment 1
XS Output Flag= 0
XS Output Increment= 10
Read HDF5 Sediment Hotstart= 0
Sediment Hotstart Type= 0
Write Gradation File= 0
Read Gradation Hotstart= 0
Write HDF5 File= 1
Write Binary Output= 1
Write DSS Sediment File= 0
DSS Sediment Output Type= 1
SV Curve= 0
Specific Gage Flag= 0
Subcell Erosion Methods= 0
Subcell Deposition Methods= 0
Advection Scheme= 1
Matrix Solver= 0
Implicit Weighting Factor= 1
Maximum Outer Loop Convergence Iterations= 5
Convergence Maximum Absolute= 0.001
Convergence RMSE= 0.0001
Grain Fractions Max Abs Error= 0.001
Max Subgrid Regions= 1
Max Subgrid Length Scale= 3.402823E+38
Initial Layer Thickness= 3.402823E+38
Min Layer Thickness= 3.402823E+38
Max Layer Thickness= 3.402823E+38
Number of Layers= 5

--- HAMILTRN.f01 (steady flow) ---

Flow Title=Flow
Program Version=6.20
Number of Profiles= 1
Profile Names=P100yr
River Rch & RM=HAMILTRN,Main,8349
     428
River Rch & RM=HAMILTRN,Main,3719
     478
River Rch & RM=HAMILTRN,Main,3211
     535
Boundary for River Rch & Prof#=HAMILTRN,Main            , 1
Up Type= 0
Dn Type= 3
Dn Slope=0.02883
DSS Import GetInterval= 0
DSS Import GetPeak= 0
DSS Import FillOption= 0

--- HAMILTRN.g01 (geometry) ---

Geom Title=Geometry
Program Version=6.20

River Reach=HAMILTRN        ,Main
Reach XY= 30
     2239621.907      574949.761      2239652.57      575080.017
     2239831.479      575204.374     2239880.618      575324.542
2240565.90163584575888.287682081     2240594.303      576027.365
     2240879.199      576252.886     2240961.152      576514.149
     2241170.344      576641.948      2241385.14       576632.15
     2241543.285      576978.174     2241625.352      577067.362
     2241782.844      577112.2612241886.84520238577423.119145843
     2242047.288      577479.585      2242215.39      577431.008
2242300.17641847577631.2305815322242798.79137321577684.226387552
     2242879.655      577847.216     2243081.803       577905.49
     2243385.449      577761.219     2243681.282      577985.177
     2244126.566      578040.594     2244292.081      577943.737
     2244455.362      577959.362 2244567.5326776577829.389065619
2244692.01241315      577878.387     2245243.261      577394.377
     2245380.563      577435.638     2245401.494      577755.241

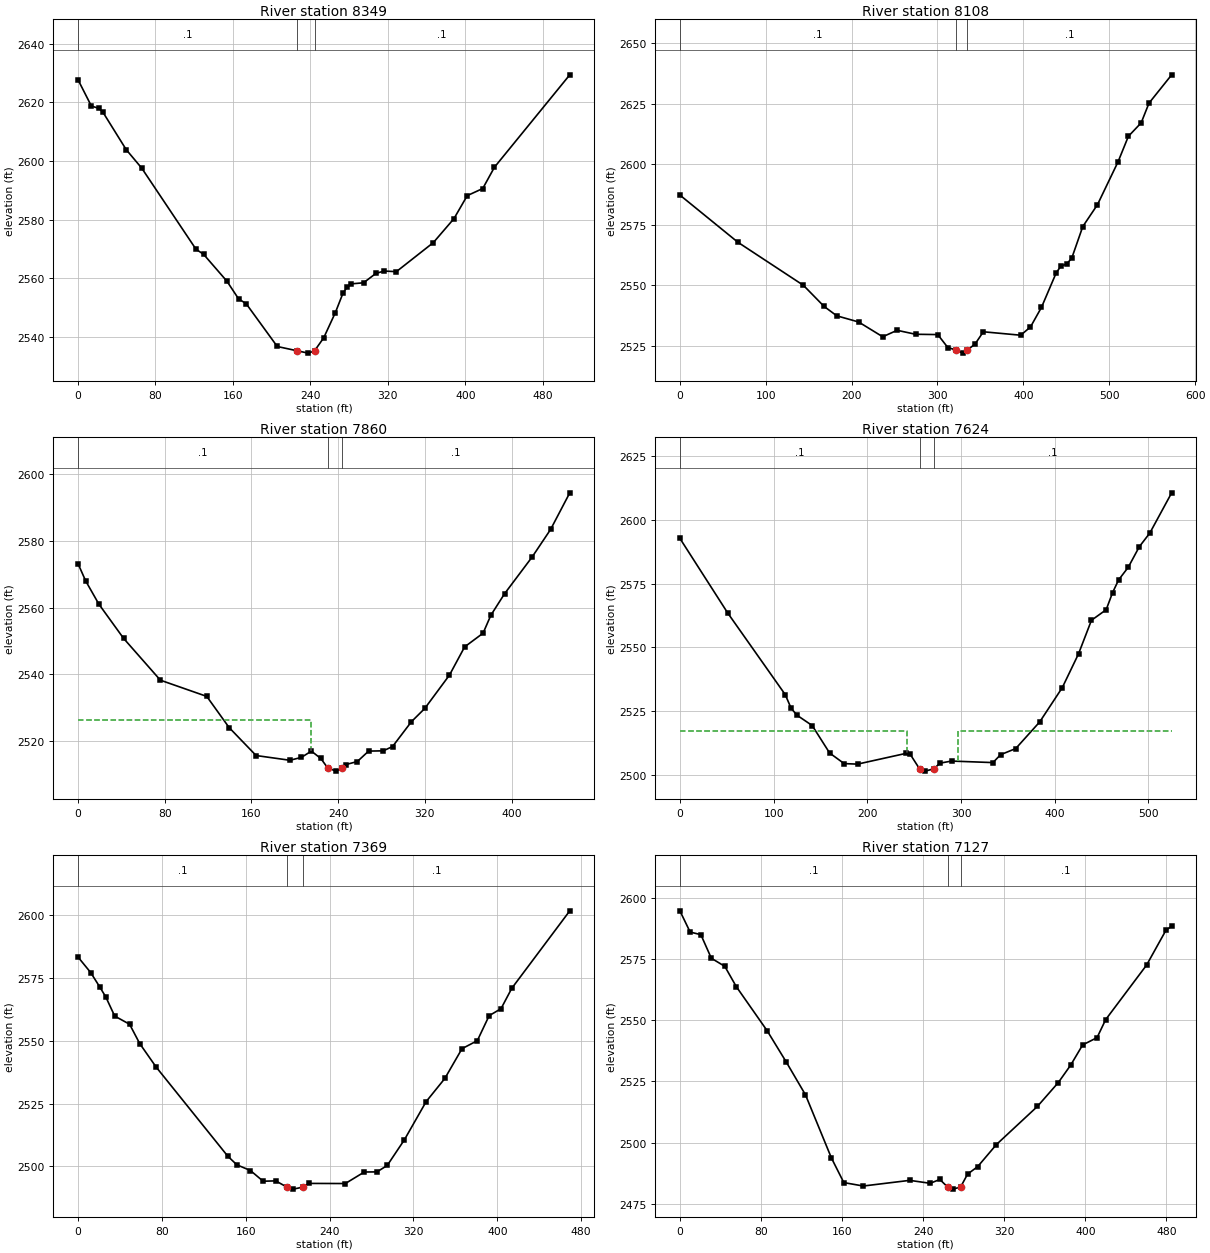
Type RM Length L Ch R = 1 ,8349    ,249.3,240.8,233.8
XS GIS Cut Line= 4
2239386.40782673574950.4825417842239583.27007514574950.918194586
2239662.44224872574952.2844463472239880.90558672574874.563657743
#Sta/Elev= 30
       0 2627.71    13.8 2618.75    21.8 2617.92    25.8 2616.61    49.8 2603.88
    65.8 2597.59   121.8 2569.97   129.8 2568.18   153.8 2559.05   165.8 2553.06
   173.8 2551.33   205.8  2536.8  226.67 2535.31   237.8 2534.54  244.26 2535.31
   253.8 2539.78   265.8 2548.36   273.8 2555.08   277.9 2557.01   282.1 2558.14
   294.9 2558.51   307.6 2561.69   316.1 2562.52   328.8  2562.3     367 2572.21
   388.3 2580.38     402 2588.21     418 2590.63   430.1 2597.89   507.9 2629.38
#Mann= 3 ,-1,0
       0      .1       0  226.67    .045       0  244.26      .1       0
Bank Sta=226.67,244.26
XS Rating Curve= 0 ,0
Exp/Cntr=0.3,0.1

Type RM Length L Ch R = 1 ,8108    ,246.2,248.1,248.5
XS GIS Cut Line= 4
2239436.84337462575207.5277390732239708.31300964 575184.20401703
2239779.33217666 575079.271947242239908.64989661574963.535472621
#Sta/Elev= 30
       0 2587.26    67.6 2567.73   143.9 2549.91   167.9 2541.21   182.7 2537.31
   208.1 2534.77   236.2 2528.65     253 2531.32   274.5 2529.68   300.3 2529.55
     312  2524.2  321.782523.143   329.3 2521.88  334.692523.143   343.7 2525.62
   353.4 2530.71   396.9 2529.29   408.3 2532.71   421.1 2540.82   438.3 2555.13
   443.7 2557.85   450.3 2558.74   456.3 2561.11   469.2 2574.24   486.3 2583.28
   510.3 2601.04   522.3 2611.56   537.2 2617.14   546.3 2625.28   572.7 2636.99
#Mann= 3 ,-1,0
       0      .1       0  321.78    .045       0  334.69      .1       0
Bank Sta=321.78,334.69
XS Rating Curve= 0 ,0
Exp/Cntr=0.3,0.1

Type RM Length L Ch R = 1 ,7860    ,242.4,236.7,232.8
XS GIS Cut Line= 4
2239727.69654236575507.9196984222239838.78158515 575372.66345159
2239919.09876456575288.079350626 2240037.2543968575177.135031639
#Sta/Elev= 30
       0 2573.25     7.1 2568.05    19.3 2561.07    42.1 2550.81      76 2538.28
   118.8 2533.41   139.4 2524.07   164.3 2515.67   195.5 2514.25   206.1 2515.11
   215.3    2517     224 2514.78  230.352511.966   237.9 2510.99  243.552511.965
   246.8 2512.93   257.7 2513.87   268.1    2517   281.6 2517.08   290.2 2518.37
   307.6 2525.82   319.9 2529.79   342.7 2539.81   356.7 2548.27   373.7 2552.38
   380.9 2557.77   393.5 2564.21     419 2575.26     436 2583.51   453.7  2594.5
#Mann= 3 ,-1,0
       0      .1       0  230.35    .045       0  243.55      .1       0
#XS Ineff= 2 , 0
           214.8 2526.38
Permanent Ineff=
       F       F
Bank Sta=230.35,243.55
XS Rating Curve= 0 ,0
Exp/Cntr=0.3,0.1

Type RM Length L Ch R = 1 ,7624    ,247.5,254.5,258.6
XS GIS Cut Line= 4
2239908.92385774575680.7153058682240060.17440244575496.272372651
2240073.13453429575369.2156218992240189.80389429575261.834522945
#Sta/Elev= 30
       0 2592.79    51.1 2563.47   112.4 2531.48   118.7 2526.12     125 2523.37
   141.2 2519.33   159.8 2508.55   175.3 2504.39   189.6 2504.19   241.6 2508.43
   245.7  2508.1   255.9 2502.25   261.7 2501.44   270.72502.313   277.8 2504.59
   289.9 2505.39   334.1 2504.79   342.2 2507.88   358.4  2510.3     384 2520.76
   408.1 2534.23   425.4 2547.46   439.2 2560.64   454.9 2564.78   461.8 2571.54
   468.2  2576.5   478.5 2581.46   490.3 2589.53   501.5 2594.88   524.8 2610.66
#Mann= 3 ,-1,0
       0      .1       0   255.9    .045       0   270.7      .1       0
#XS Ineff= 2 , 0
           242.6 2517.17  296.32         2517.38
Permanent Ineff=
       F       F
Bank Sta=255.9,270.7
XS Rating Curve= 0 ,0
Exp/Cntr=0.3,0.1

Type RM Length L Ch R = 1 ,7369    ,243.9,242.2,240.8
XS GIS Cut Line= 4
2240088.16339282575806.4582170222240186.19704655575688.627502151
 2240289.3320253575597.2765307712240419.05940956575475.278944769
#Sta/Elev= 30
       0 2583.21    12.1 2577.04    20.8 2571.28    26.5 2567.36      35 2559.75
    49.2 2556.51    58.9 2548.81    74.5 2539.52   142.9 2504.08   151.5 2500.68
   164.5 2498.39   176.6 2494.15   188.6 2494.29  199.322491.808   205.3 2491.01
  214.552491.808     220 2493.28     255 2493.23   273.1 2497.81   285.2 2497.86
     295 2500.43   311.4 2510.65   332.1 2525.78   349.9 2534.96   366.3  2546.8
   380.9 2549.98   392.2 2559.92   403.5 2562.68   413.8  2570.8   469.1 2601.56
#Mann= 3 ,-1,0
       0      .1       0  199.32    .045       0  214.55      .1       0
Bank Sta=199.32,214.55
XS Rating Curve= 0 ,0
Exp/Cntr=0.3,0.1

Type RM Length L Ch R = 1 ,7127    ,241.8,246.3,250.8
XS GIS Cut Line= 4
2240228.12598885575987.3948105092240352.28525809575886.629070628
2240432.21364667575779.1528938522240557.35450371575634.458724942
#Sta/Elev= 30
       0 2594.67    10.1    2586    20.7 2584.93      31 2575.31    44.3 2571.99
    55.6 2563.73      86 2545.74   105.1  2532.8   123.9  2519.5   149.5 2493.69
   161.7 2483.66   180.9 2482.26   226.7 2484.57   246.9 2483.37   256.4 2484.94
  264.06 2481.87   269.5 2480.99  276.932481.874   283.8 2487.13   293.8  2490.2
   312.2 2499.19   352.7 2514.79   373.3 2524.53   385.5 2531.65   397.3  2539.9
   411.5 2542.87     420 2550.23   460.4 2572.53   479.5 2586.76   485.1 2588.39
#Mann= 3 ,-1,0
       0      .1       0  264.06    .045       0  276.93      .1       0
Bank Sta=264.06,276.93
XS Rating Curve= 0 ,0
Exp/Cntr=0.3,0.1

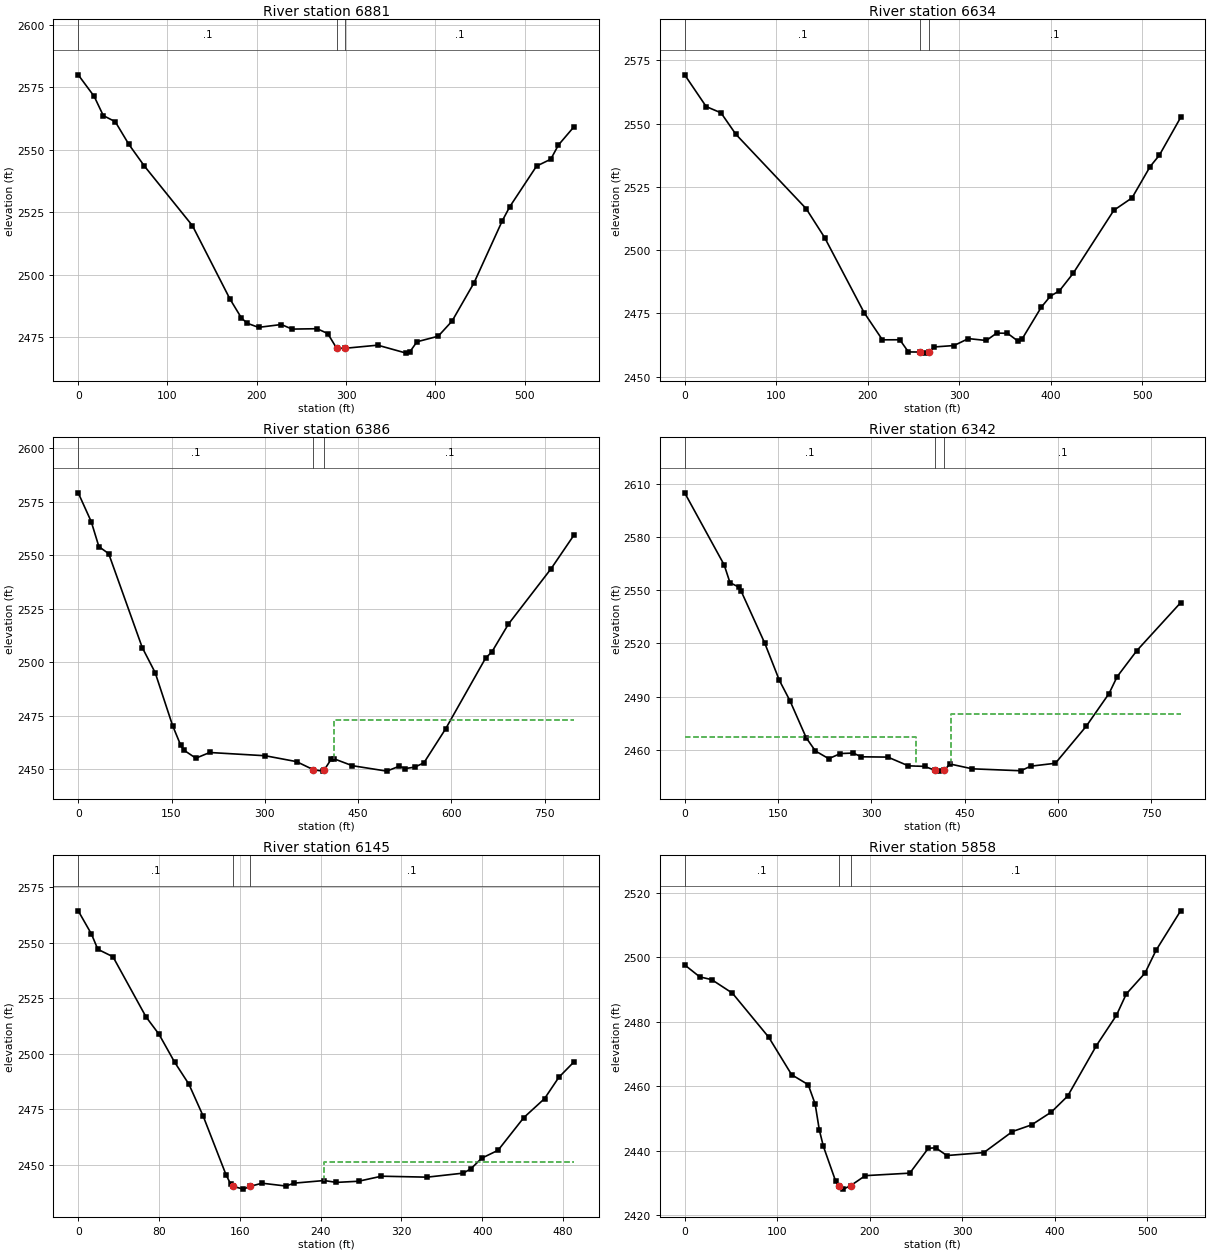
Type RM Length L Ch R = 1 ,6881    ,249.5,246.8,242.5
XS GIS Cut Line= 4
 2240318.1899229576091.0264362852240496.53269639575949.146596038
2240652.79585622575949.0219808362240754.95003604575811.377145484
#Sta/Elev= 30
       0 2579.97    17.9 2571.34    28.1 2563.67    41.5 2561.23    56.8 2552.13
    74.1 2543.51     128 2519.63     170 2490.33   182.9 2482.73   189.3 2480.65
     202    2479   227.6 2480.14   239.5 2478.31   267.6 2478.46   279.5 2476.54
  289.542470.653   299.4 2470.65   335.5 2471.88   367.5  2468.7   371.5 2469.19
   379.5 2473.24   403.3 2475.46   418.8  2481.5   443.5 2496.86   475.1 2521.63
   483.6 2527.31   513.5 2543.48   529.4 2546.23     538 2551.92   555.6 2559.28
#Mann= 3 ,-1,0
       0      .1       0  289.54    .045       0   299.4      .1       0
Bank Sta=289.54,299.4
XS Rating Curve= 0 ,0
Exp/Cntr=0.3,0.1

Type RM Length L Ch R = 1 ,6634    ,234.9,247.5,253.4
XS GIS Cut Line= 4
2240494.01652808576291.6275257132240673.56971102576168.445526428
2240785.35444668576073.8671350082240890.72710271575930.385529683
#Sta/Elev= 30
       0 2569.26    23.5 2556.72    39.7 2554.24      56 2545.75   132.8 2516.38
     153 2504.97   196.1 2475.35   216.2 2464.55   235.2 2464.58   244.6 2459.77
   257.8 2459.73   263.1  2459.3   267.3 2459.74     273 2461.74   294.5  2462.3
   310.2 2465.04   329.8 2464.29   341.1 2467.21   352.9 2467.14   364.2  2464.1
   368.9 2464.89   389.8 2477.41   399.8 2481.82   409.7 2483.92   424.6 2490.77
   469.2 2515.74   489.1 2520.65   508.9 2533.03   518.9 2537.47   542.2  2552.4
#Mann= 3 ,-1,0
       0      .1       0   257.8    .045       0   267.3      .1       0
Bank Sta=257.8,267.3
XS Rating Curve= 0 ,0
Exp/Cntr=0.3,0.1

Type RM Length L Ch R = 1 ,6386    ,47.9,44.7,45.3
XS GIS Cut Line= 6
2240659.04750063576451.1245503962240798.25605035576220.137752765
2240880.04799786576279.5304758242240909.71979174  576294.6103858
2240980.95292859  576318.6249511  2241169.354389576062.603793285
#Sta/Elev= 30
       0 2579.05      21 2565.55    33.2 2553.95      49 2550.64   102.9 2506.83
   123.7  2495.1   151.7 2470.39   164.9 2461.09   170.4  2458.8   189.1 2455.15
   211.4 2457.81   300.7 2456.29   350.9 2453.55   378.1 2449.76     393 2449.11
   395.7 2449.77   406.8 2454.74     411 2454.89   440.6 2451.65     496 2449.11
   515.9 2451.39   525.8 2450.32   540.7 2450.96   555.6 2452.95   590.4 2468.76
     655 2501.96   664.9 2504.75   691.5 2517.74   760.2 2543.65   797.2 2559.45
#Mann= 3 ,-1,0
       0      .1       0   378.1    .045       0   395.7      .1       0
#XS Ineff= 2 , 0
                          410.69         2472.83
Permanent Ineff=
       F       F
Bank Sta=378.1,395.7
XS Rating Curve= 0 ,0
Exp/Cntr=0.3,0.1

Type RM Length L Ch R = 1 ,6342    ,201.6,196.8,188.4
XS GIS Cut Line= 6
2240642.12013603576487.5442521822240781.32868575576256.557454552
2240863.12063326 576315.950177612240892.79242714576331.030087587
2240964.02556399576355.044652886 2241152.4270244576099.023495071
#Sta/Elev= 30
       0  2604.8    63.5 2564.19    72.8 2554.21    86.8 2551.72    90.6 2549.55
   128.9 2519.97   152.2 2499.17   169.3 2487.62   195.5 2466.72   210.1  2459.4
   231.6 2455.03   250.3 2457.93   270.9 2458.21   283.8  2456.1   326.6 2455.93
   359.6 2451.01   385.5 2450.71   402.3  2448.5   408.4 2448.03  417.48 2448.51
   426.2 2452.07   462.3 2449.33   540.3 2448.24   556.2 2450.81   595.9 2452.46
   645.6 2473.37   682.1 2491.73   695.2 2501.25   726.8  2515.9   797.2  2542.9
#Mann= 3 ,-1,0
       0      .1       0   402.3    .045       0  417.48      .1       0
#XS Ineff= 2 , 0
          372.45 2467.22  428.01         2480.03
Permanent Ineff=
       F       F
Bank Sta=402.3,417.48
XS Rating Curve= 0 ,0
Exp/Cntr=0.3,0.1

Type RM Length L Ch R = 1 ,6145    ,296.1,286.6,280.5
XS GIS Cut Line= 4
2240843.33712461576623.0303288042240939.60007279576513.692993078
2241019.15892988 576470.597777852241189.51788468576281.152919089
#Sta/Elev= 30
       0 2564.34    13.1 2553.89    19.4 2547.02    34.4 2543.66    67.1 2516.59
      80 2508.73    95.4  2496.2   109.6 2486.24   123.8 2471.78   146.3 2445.49
   150.9 2441.28   153.62440.204   163.6 2439.01     1702440.227   181.9 2441.68
   205.5 2440.41   213.9 2441.71   243.4 2442.88   255.6 2442.04   277.5 2442.56
   300.2 2444.83   345.4  2444.4   381.2 2446.22   388.7 2448.18   399.4 2452.94
   415.6 2456.51   441.1 2471.24   461.6 2479.77   475.8  2489.4   490.9 2496.39
#Mann= 3 ,-1,0
       0      .1       0   153.6    .045       0     170      .1       0
#XS Ineff= 2 , 0
                           243.4         2451.28
Permanent Ineff=
       F       F
Bank Sta=153.6,170
XS Rating Curve= 0 ,0
Exp/Cntr=0.3,0.1

Type RM Length L Ch R = 1 ,5858    ,128.6,122.2,115.5
XS GIS Cut Line= 4
2241116.51483157576803.3202148842241188.91422373576658.335340081
 2241182.2478385576475.1420746542241309.98557511576333.637649999
#Sta/Elev= 30
       0 2497.67    16.3 2493.95    29.2  2493.1    51.6  2488.9    90.8 2475.25
   115.6 2463.61   133.5 2460.52     141 2454.53   145.5  2446.5   149.9 2441.39
   163.2 2430.56   166.6 2429.22   171.6 2428.12  179.462429.219   195.2  2432.3
   243.3 2433.08   263.3 2440.79   271.3 2440.95   283.3 2438.54   323.3 2439.45
   354.2 2445.98     375 2448.06   396.3 2452.03   413.9 2456.97     445 2472.64
   466.6 2482.02   477.3 2488.67   497.5 2495.12   509.4 2502.18     536 2514.44
#Mann= 3 ,-1,0
       0      .1       0   166.6    .045       0  179.46      .1       0
Bank Sta=166.6,179.46
XS Rating Curve= 0 ,0
Exp/Cntr=0.3,0.1

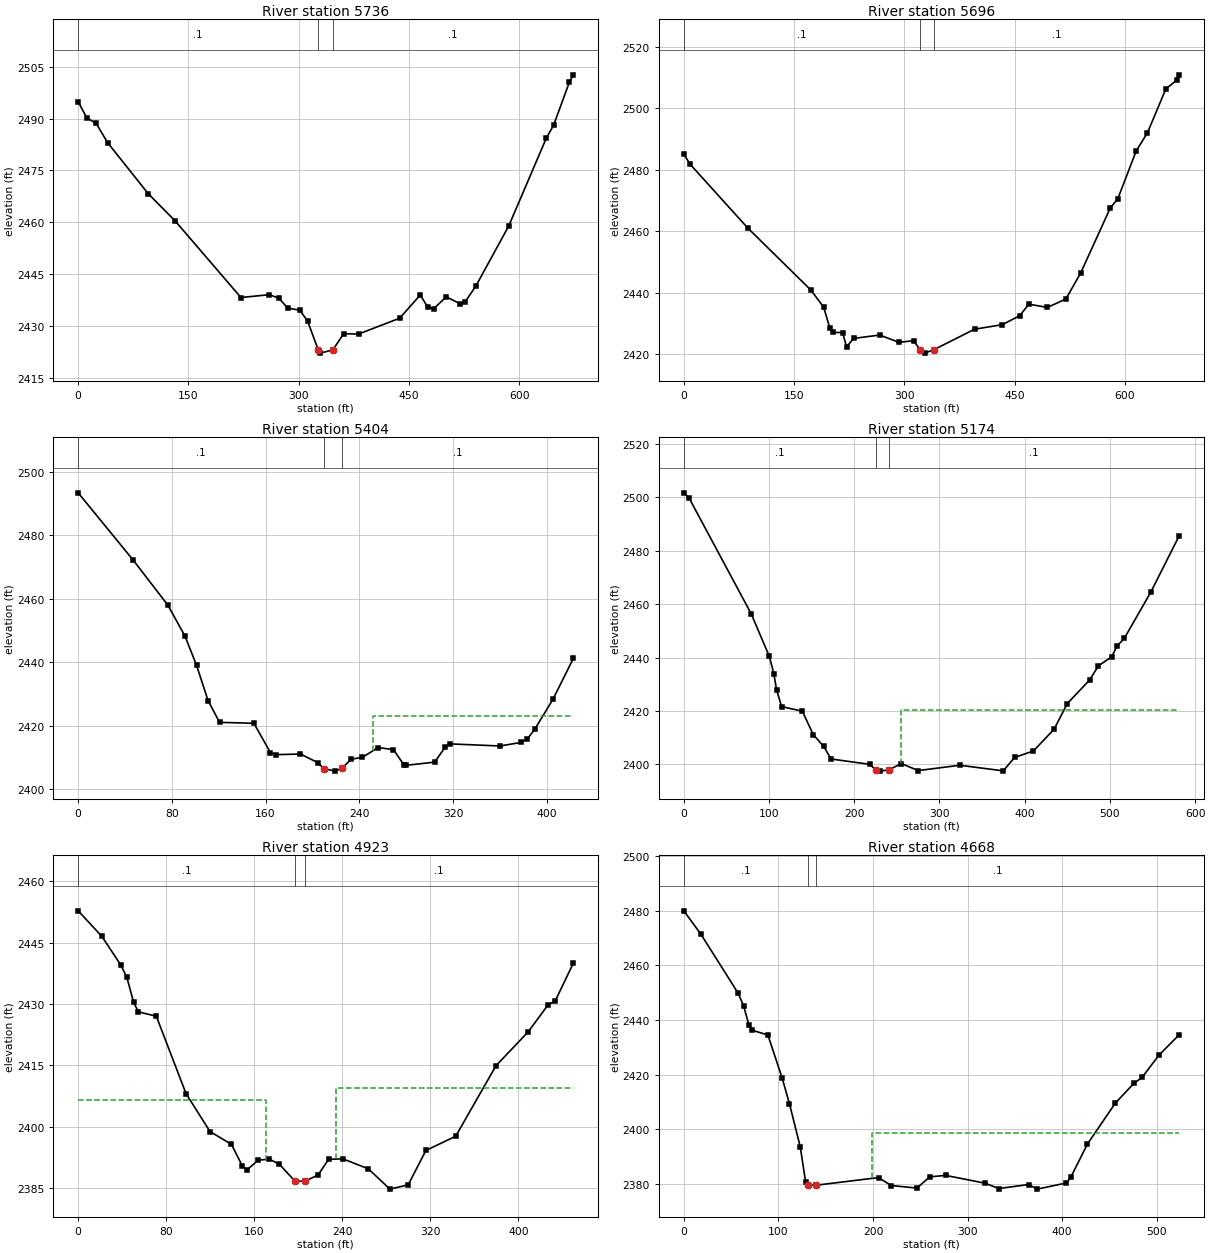
Type RM Length L Ch R = 1 ,5736    ,41.7,40.2,42
XS GIS Cut Line= 6
2241153.31452612576815.7357664232241359.70900993576735.288006273
2241339.45182051576667.9599166672241277.43438623576604.157691874
2241211.20960852576553.5822556762241338.24031157 576387.77770529
#Sta/Elev= 30
       0 2494.92    11.7 2490.23    24.5 2488.64    40.1 2483.03    95.2 2468.29
   131.9 2460.38   221.5 2438.18   260.3 2439.01   273.2 2437.96   285.1 2435.11
   301.5 2434.52   312.2 2431.35  326.672422.999     329 2422.07  346.542422.998
   361.2 2427.69   381.7 2427.61   437.5 2432.19   465.5 2438.92   475.6 2435.41
   483.5 2434.86   500.8  2438.4   519.2 2436.41     526 2436.77   541.1 2441.49
   585.8 2458.88   637.1  2484.4   646.9 2488.09   668.5 2500.63   673.8  2502.7
#Mann= 3 ,-1,0
       0      .1       0  326.67    .045       0  346.54      .1       0
Bank Sta=326.67,346.54
XS Rating Curve= 0 ,0
Exp/Cntr=0.3,0.1

Type RM Length L Ch R = 1 ,5696    ,271.5,291.8,302.7
XS GIS Cut Line= 6
2241190.90454875576806.9369565912241397.29903256 576726.48919644
2241377.04184314576659.1611068352241315.02440886576595.358882042
2241248.79963115576544.783445844 2241375.8303342576378.978895458
#Sta/Elev= 30
       0 2485.13     8.5 2481.84    87.2 2460.99   173.1 2440.77   190.3 2435.22
   198.8 2428.36   203.1 2427.03     216 2426.95   221.5 2422.36   231.2 2425.06
   266.6 2426.15   292.6 2423.79   312.6 2424.29  321.372421.419   327.9 2420.26
  340.682421.419   395.6 2428.05   433.5 2429.54   457.2 2432.48   469.5 2436.21
   494.7 2435.15   519.9 2437.89   540.1 2446.42   580.4  2467.6   590.5 2470.53
   615.6 2486.16   630.8 2492.01     656  2506.4   671.1 2509.25   673.8 2510.95
#Mann= 3 ,-1,0
       0      .1       0  321.37    .045       0  340.68      .1       0
Bank Sta=321.37,340.68
XS Rating Curve= 0 ,0
Exp/Cntr=0.3,0.1

Type RM Length L Ch R = 1 ,5404    ,230.5,229.6,228
XS GIS Cut Line= 4
2241309.61401862 576978.157130432241437.88025435576887.582455321
2241525.24338706576838.4941275052241675.85500663576769.837434016
#Sta/Elev= 30
       0 2493.29    47.2 2472.02    76.6 2457.94    91.3 2448.14   101.1 2438.99
   110.9 2427.93   120.7 2421.07     150 2420.79   164.2 2411.55   169.3 2410.91
   189.8 2411.11   204.5 2408.43  209.72 2406.55   219.2 2405.73   225.1 2406.56
   233.1 2409.49   242.7 2410.06     256 2413.14   269.2 2412.51     278 2407.74
   279.7 2407.55   304.4 2408.56   313.2  2413.2   317.6  2414.3   360.1 2413.64
   378.2 2414.76   383.5 2415.86   389.8 2418.88   405.4 2428.35   422.8 2441.19
#Mann= 3 ,-1,0
       0      .1       0  209.72    .045       0   225.1      .1       0
#XS Ineff= 2 , 0
                           251.7          2423.1
Permanent Ineff=
       F       F
Bank Sta=209.72,225.1
XS Rating Curve= 0 ,0
Exp/Cntr=0.3,0.1

Type RM Length L Ch R = 1 ,5174    ,249.8,251.6,251
XS GIS Cut Line= 4
2241402.69953315577152.6138779392241555.78222138577092.399623956
2241749.29706443576938.4753655552241858.18694498576808.746906993
#Sta/Elev= 30
       0 2501.71     5.9 2499.94      79 2456.46   100.4 2440.43   105.6 2434.02
     109 2427.77   114.8 2421.65   139.1 2419.92   151.9 2411.15   164.2 2406.72
   172.8 2402.03   218.3 2400.01  225.192397.957   229.7 2397.48   240.4 2397.94
   255.3 2400.29   275.2 2397.69   323.9 2399.68   374.9 2397.58   388.1 2402.59
   410.3 2405.03   434.6  2413.2     450 2422.77   476.1 2431.57   486.6 2436.91
   502.2 2440.35   508.4 2444.33   516.9 2447.19   548.2 2464.63   581.1 2485.45
#Mann= 3 ,-1,0
       0      .1       0  225.19    .045       0   240.4      .1       0
#XS Ineff= 2 , 0
                          255.16         2420.55
Permanent Ineff=
       F       F
Bank Sta=225.19,240.4
XS Rating Curve= 0 ,0
Exp/Cntr=0.3,0.1

Type RM Length L Ch R = 1 ,4923    ,255.6,254.6,253
XS GIS Cut Line= 4
2241635.77319984577275.1786526382241741.80138432577178.283312121
2241833.55606997577160.0058971962241991.76247266577017.712004122
#Sta/Elev= 30
       0 2452.76    21.5 2446.53    38.5 2439.61    44.2 2436.56    50.4 2430.39
    54.7 2428.07      71 2427.01      98  2408.1   119.8 2398.83   139.3 2395.69
   149.3 2390.34   153.4 2389.43   163.6 2391.84   173.8 2392.05   182.8 2390.85
     1972386.694   206.12386.689     218  2388.2   227.6 2392.04   240.7 2392.14
   263.7 2389.71   283.3 2384.75   299.9  2385.8     316  2394.2   343.1 2397.68
   379.8 2414.95   408.9 2423.16   426.8  2429.7   433.6  2430.8     450 2439.97
#Mann= 3 ,-1,0
       0      .1       0     197    .045       0   206.1      .1       0
#XS Ineff= 2 , 0
          170.73 2406.62   234.3         2409.38
Permanent Ineff=
       F       F
Bank Sta=197,206.1
XS Rating Curve= 0 ,0
Exp/Cntr=0.3,0.1

Type RM Length L Ch R = 1 ,4668    ,245.2,233.2,223.6
XS GIS Cut Line= 4
2241765.92170938577483.5531101362241866.30498503577406.131522782
 2242039.8228005577314.6820648352242126.95471682577134.083157009
#Sta/Elev= 30
       0 2479.91      18 2471.39    57.5 2449.72    63.2 2445.15    68.9 2438.05
    71.7 2436.27    88.9 2434.45   103.9 2418.78   111.7 2409.28   123.1  2393.5
   128.8  2380.6  131.342379.494  139.722379.492   205.8 2382.28   219.3 2379.38
   246.4 2378.44     260 2382.57   276.9 2383.08   318.8  2380.2   332.9 2378.27
   364.6 2379.75   373.4 2378.06   404.5 2380.31     409  2382.4   426.7 2394.59
   456.1 2409.53   475.6 2416.72   484.5 2418.99   502.2 2427.09   523.4 2434.47
#Mann= 3 ,-1,0
       0      .1       0  131.34    .045       0  139.72      .1       0
#XS Ineff= 2 , 0
                          198.84         2398.69
Permanent Ineff=
       F       F
Bank Sta=131.34,139.72
XS Rating Curve= 0 ,0
Exp/Cntr=0.3,0.1

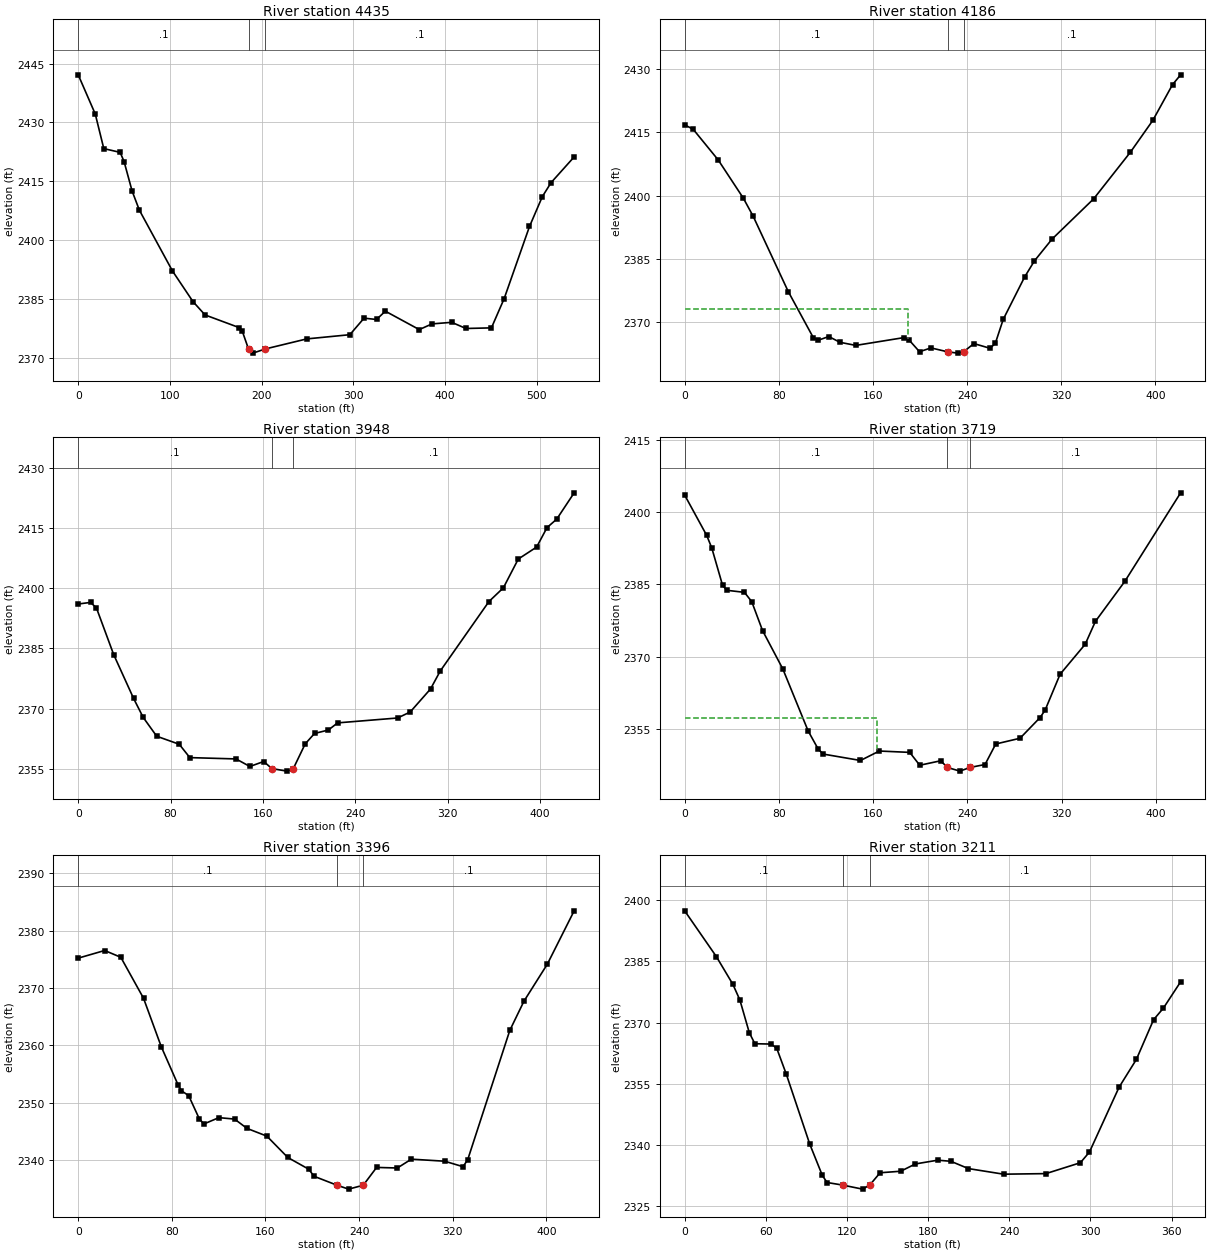
Type RM Length L Ch R = 1 ,4435    ,236.6,248.9,260.9
XS GIS Cut Line= 4
2242016.75134805577650.4768659492242088.80816901577496.461153847
2242024.25973658577382.2796105952242144.81981668577175.253100408
#Sta/Elev= 30
       0 2442.12    18.6 2432.14    27.9 2423.34    45.7 2422.39      50 2420.06
    58.8 2412.52    66.7 2407.67   102.8 2392.19   125.1 2384.42   138.3 2381.01
   175.8 2377.76   178.8 2376.95   185.7 2372.34   190.5 2371.29   203.8 2372.34
   249.2 2374.91   296.2 2375.98   311.7 2380.19   325.3 2379.85   334.9 2381.97
   371.9 2377.28   385.8 2378.73   407.3 2379.13   422.8 2377.56   450.6 2377.72
   464.5 2385.18   492.1 2403.52   506.1 2411.12   515.6 2414.67   540.8 2421.23
#Mann= 3 ,-1,0
       0      .1       0   185.7    .045       0   203.8      .1       0
Bank Sta=185.7,203.8
XS Rating Curve= 0 ,0
Exp/Cntr=0.3,0.1

Type RM Length L Ch R = 1 ,4186    ,247.8,238,229.1
XS GIS Cut Line= 4
2242136.52638429577655.9837614632242174.30064192577551.328399937
2242314.06065388577474.5221068762242359.05170181577330.659021786
#Sta/Elev= 30
       0 2416.74     7.2 2415.71    28.5 2408.43    49.8  2399.4    58.2  2395.1
      88 2377.26   109.3 2366.34   113.4 2365.71   122.5 2366.59   131.9 2365.23
   145.4 2364.49   186.4 2366.34     191 2365.68   199.6 2362.99   209.3  2363.9
   223.42362.974     232 2362.66     2372362.968   245.8 2364.92   259.5 2363.81
     264 2364.96   270.7 2370.64   288.9 2380.69   297.3 2384.53   312.2 2389.67
   347.6 2399.22   378.9  2410.3   397.9 2417.82   414.6 2426.27   421.5  2428.6
#Mann= 3 ,-1,0
       0      .1       0   223.4    .045       0     237      .1       0
#XS Ineff= 2 , 0
          189.53 2373.16
Permanent Ineff=
       F       F
Bank Sta=223.4,237
XS Rating Curve= 0 ,0
Exp/Cntr=0.3,0.1

Type RM Length L Ch R = 1 ,3948    ,223.5,228.4,230.3
XS GIS Cut Line= 4
2242329.00736577577777.5395042982242387.05354667577704.937793189
2242389.40410138577502.6867761072242430.77502507577374.783091786
#Sta/Elev= 30
       0 2396.08    10.7 2396.48    15.8 2395.09    30.7 2383.48      48 2372.52
    56.3  2367.8      68 2363.11    87.5 2361.11    96.7 2357.78   136.7 2357.45
   148.7 2355.57   160.7 2356.81  167.72 2355.05   180.7 2354.41  186.33 2355.04
   196.6 2361.19   204.7  2363.8   216.7 2364.66   224.7 2366.44   276.7 2367.66
   287.6 2369.16   305.2  2374.9   313.6 2379.37   355.8  2396.7   368.3 2400.12
   381.2 2407.29   397.1 2410.28   406.1 2415.13   414.5 2417.24   429.6  2423.8
#Mann= 3 ,-1,0
       0      .1       0  167.72    .045       0  186.33      .1       0
Bank Sta=167.72,186.33
XS Rating Curve= 0 ,0
Exp/Cntr=0.3,0.1

Type RM Length L Ch R = 1 ,3719    ,317.4,323.8,333.7
XS GIS Cut Line= 4
2242507.60321798577902.5239935352242578.11057707577726.229762928
2242603.10997918577657.7709610712242656.65489815577508.918677182
#Sta/Elev= 30
       0 2403.55    18.7 2395.18      23 2392.58    32.2 2384.79    35.9 2383.79
    50.7 2383.37    56.9 2381.45    66.1 2375.43    83.3 2367.47   104.8  2354.6
   113.5 2350.76   117.8  2349.8   149.2 2348.48   165.2 2350.44     191 2350.16
   199.5 2347.49   217.3 2348.42  222.95 2347.03   233.6 2346.27   242.1 2347.03
   254.9 2347.64     264  2351.9   284.6 2353.09   301.6 2357.38   305.9 2358.93
   318.6 2366.37   339.9 2372.59   348.6 2377.35   373.5 2385.63   420.9 2404.02
#Mann= 3 ,-1,0
       0      .1       0  222.95    .045       0   242.1      .1       0
#XS Ineff= 2 , 0
          163.39 2357.23
Permanent Ineff=
       F       F
Bank Sta=222.95,242.1
XS Rating Curve= 0 ,0
Exp/Cntr=0.3,0.1

Type RM Length L Ch R = 1 ,3396    ,189.7,185.2,173.7
XS GIS Cut Line= 4
2242689.58580719577934.3024256552242783.83724408577815.158514051
2242885.51661983577764.1637314912242895.78266812577606.320666759
#Sta/Elev= 30
       0 2375.19    22.6 2376.52    36.4 2375.34    55.8 2368.21      71 2359.75
    85.2 2353.18    88.1 2352.11    94.4 2351.24   103.4 2347.24   107.3  2346.3
   120.2 2347.41   133.6 2347.16   144.2 2345.54   161.2 2344.19   179.1 2340.47
     197 2338.43   201.5  2337.2   221.42335.622   231.1 2334.96  243.57 2335.64
     255 2338.74   272.7 2338.64   284.7 2340.18   313.2 2339.82   328.8 2338.87
   332.8 2340.06   368.8  2362.6   380.9 2367.69   400.9 2374.15   423.8 2383.43
#Mann= 3 ,-1,0
       0      .1       0   221.4    .045       0  243.57      .1       0
Bank Sta=221.4,243.57
XS Rating Curve= 0 ,0
Exp/Cntr=0.3,0.1

Type RM Length L Ch R = 1 ,3211    ,264.6,251.3,241.2
XS GIS Cut Line= 4
2242959.57362471577984.152372388 2242977.2836528577889.355358989
2243037.18460216 577749.907401192243073.09204029577636.994948798
#Sta/Elev= 30
       0 2397.38    23.4 2386.18    35.6  2379.4    40.8 2375.56    47.8 2367.51
    51.9 2364.83    64.1 2364.74    68.1 2363.68    75.1  2357.4    92.5 2340.22
   101.8 2332.55   105.3 2330.83  116.892330.199   131.5 2329.21  136.812330.197
   144.5 2333.22   159.7 2333.59   170.6 2335.38   187.1  2336.3   196.8 2336.03
   209.8 2334.24   235.8 2332.87   267.1 2333.01   292.6 2335.68   299.3  2338.3
   321.2 2354.18     334 2360.99   346.7 2370.71   353.9 2373.52   366.7 2379.99
#Mann= 3 ,-1,0
       0      .1       0  116.89    .045       0  136.81      .1       0
Bank Sta=116.89,136.81
XS Rating Curve= 0 ,0
Exp/Cntr=0.3,0.1

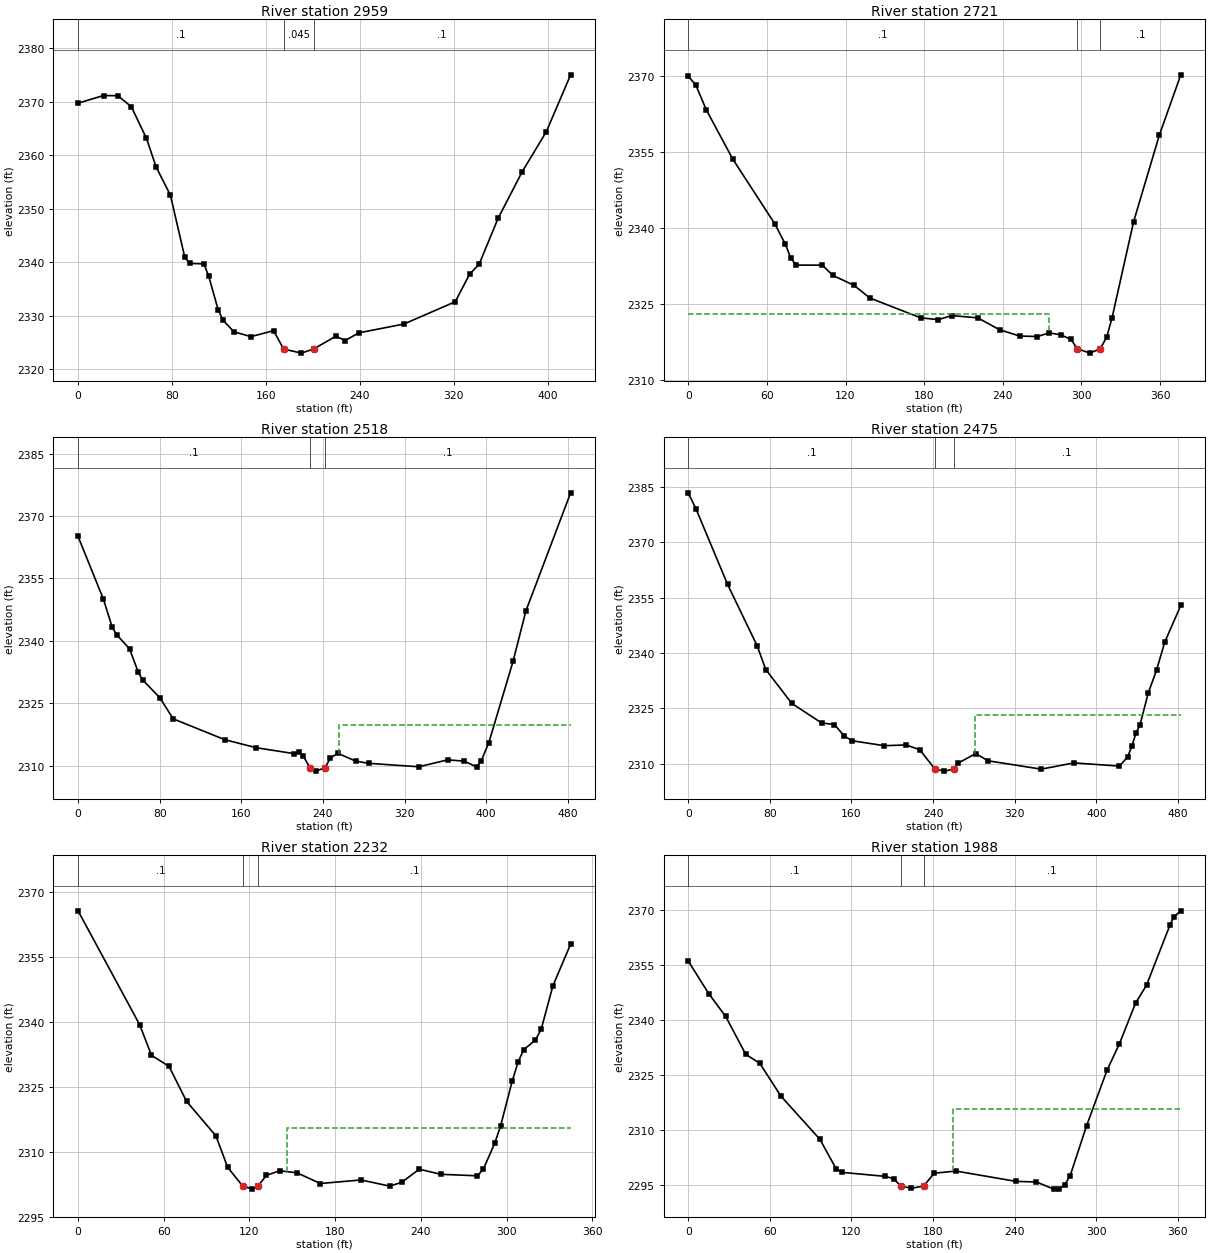
Type RM Length L Ch R = 1 ,2959    ,229.7,238.2,248.2
XS GIS Cut Line= 4
2243236.33967395 578054.449008572243259.97105193577931.257957136
 2243164.2089728577789.4387186882243188.62207623577668.814943948
#Sta/Elev= 30
       0 2369.74    21.7 2371.17    33.9 2371.13    45.4 2369.08    58.3 2363.15
    66.5 2357.83    78.7 2352.53    90.9 2340.95      95 2339.79   107.2  2339.7
   111.3 2337.41   119.4 2331.08   123.5 2329.17   132.8 2327.01   147.3  2326.1
   166.6 2327.22   175.1 2323.79   190.2 2323.02  200.67 2323.79   219.6 2326.18
   227.6 2325.37     239  2326.8   277.6 2328.46   321.3 2332.62   333.6 2337.79
   341.7 2339.66   357.8 2348.21   378.4 2356.95   398.9 2364.41   419.6 2375.04
#Mann= 3 ,-1,0
       0      .1       0   175.1    .045       0  200.67      .1       0
Bank Sta=175.1,200.67
XS Rating Curve= 0 ,0
Exp/Cntr=0.3,0.1

Type RM Length L Ch R = 1 ,2721    ,199.5,203.4,211.2
XS GIS Cut Line= 4
2243330.55581973578058.9451421782243345.81781833577909.430139324
 2243418.2235555577761.5684511362243423.98646934577700.997009963
#Sta/Elev= 30
       0 2370.01     5.8 2368.27    13.8 2363.38    33.9 2353.69    66.1 2340.85
    74.1 2336.86    78.2 2334.14    82.2 2332.72   102.3 2332.71   110.3 2330.69
   126.4 2328.75   138.5 2326.23   177.3 2322.31   190.7 2321.95   201.1 2322.76
     221  2322.3   237.5 2319.96     253 2318.71   266.4 2318.62   275.3 2319.33
   284.2 2318.96   292.1 2318.04  296.812316.222   306.5 2315.34  314.422316.222
   319.3 2318.52   323.4 2322.36   339.8 2341.29   359.5 2358.43   375.8 2370.29
#Mann= 3 ,-1,0
       0      .1       0  296.81    .045       0  314.42      .1       0
#XS Ineff= 2 , 0
          275.05 2323.15
Permanent Ineff=
       F       F
Bank Sta=296.81,314.42
XS Rating Curve= 0 ,0
Exp/Cntr=0.3,0.1

Type RM Length L Ch R = 1 ,2518    ,42.3,43.2,43.1
XS GIS Cut Line= 6
2243431.54708324578060.4971240432243477.38714421577938.103131847
2243625.25254261 577878.352574052243650.43088872577877.799203806
2243668.69210678577881.1194252712243687.92424405577733.665156529
#Sta/Elev= 30
       0  2365.1    24.9 2349.98    33.4 2343.31    37.7 2341.51    50.5 2338.06
    59.1 2332.39    63.3 2330.61    80.4 2326.25    93.2 2321.24   143.8 2316.23
   174.8 2314.29   211.9 2312.87   216.2 2313.23   220.5 2312.39   227.2 2309.52
   233.2 2308.67  242.11 2309.52   247.3 2311.83   254.5 2312.96   272.2 2311.07
   284.9 2310.54     334 2309.72   362.2 2311.38   378.3 2311.08   390.6 2309.69
   394.9 2311.04   402.5 2315.49   426.3 2335.07   438.8 2347.14   482.7 2375.58
#Mann= 3 ,-1,0
       0      .1       0   227.2    .045       0  242.11      .1       0
#XS Ineff= 2 , 0
                           255.6         2319.86
Permanent Ineff=
       F       F
Bank Sta=227.2,242.11
XS Rating Curve= 0 ,0
Exp/Cntr=0.3,0.1

Type RM Length L Ch R = 1 ,2475    ,247.3,242.7,234.6
XS GIS Cut Line= 6
2243446.62357498578096.3647785392243492.46363595577973.970786343
2243640.32903435577914.2202285472243665.50738046577913.666858303
2243683.76859852577916.9870797682243703.00073579577769.532811026
#Sta/Elev= 30
       0 2383.46     7.7 2379.06    38.6 2358.59    67.5 2341.99      76 2335.51
   101.6  2326.3   130.7 2321.02   143.3  2320.6   152.6 2317.56   160.6 2316.19
   192.2 2314.85   213.5 2315.05   226.8 2313.77  241.872308.496     251 2307.95
   260.1 2308.48   264.4  2310.1   281.6  2312.7   294.1 2310.74   345.9 2308.49
   378.2 2310.18   422.6 2309.31   430.6  2311.8   434.7 2314.68   438.7  2318.2
   442.8 2320.58   450.8 2329.16   458.9 2335.32     467 2342.97   482.7 2352.91
#Mann= 3 ,-1,0
       0      .1       0  241.87    .045       0   260.1      .1       0
#XS Ineff= 2 , 0
                          280.87         2323.28
Permanent Ineff=
       F       F
Bank Sta=241.87,260.1
XS Rating Curve= 0 ,0
Exp/Cntr=0.3,0.1

Type RM Length L Ch R = 1 ,2232    ,241.3,244.1,242.2
XS GIS Cut Line= 4
2243786.03339923578147.3101690192243809.56248431578042.945853312
2243826.32614773578013.0317071832243863.80588768577813.028485871
#Sta/Elev= 30
       0 2365.71    43.2 2339.33    51.4 2332.28    63.7 2329.73      76 2321.62
    96.5 2313.66   104.7  2306.4   115.22302.074     122 2301.34   126.12302.105
   131.9 2304.53   141.1 2305.59   153.3 2305.11   169.6 2302.64   198.1 2303.46
   218.1 2302.04   226.6 2302.91   238.8 2305.95     254 2304.77   279.5 2304.42
   283.6 2305.89   291.7 2311.97   295.8 2315.98   303.9 2326.33     308 2330.71
     312 2333.61   320.2 2335.83   324.3 2338.44   332.4 2348.37   344.8 2358.01
#Mann= 3 ,-1,0
       0      .1       0   115.2    .045       0   126.1      .1       0
#XS Ineff= 2 , 0
                          146.32         2315.57
Permanent Ineff=
       F       F
Bank Sta=115.2,126.1
XS Rating Curve= 0 ,0
Exp/Cntr=0.3,0.1

Type RM Length L Ch R = 1 ,1988    ,309.2,305.5,301.5
XS GIS Cut Line= 4
2243997.37730547578184.1246880392244018.33122144 578078.00126704
2244040.62250379578014.2626595642244046.97356542577828.016570049
#Sta/Elev= 30
       0 2355.96    15.2 2347.01    27.5 2340.88    42.3 2330.53    52.6 2328.08
    68.2 2319.12    96.8 2307.37     109 2299.16   113.3 2298.35   144.8 2297.27
   151.1 2296.63  156.142294.645   164.1 2294.02   173.1 2294.63   180.8 2298.12
   196.8 2298.72   240.8 2295.91     256 2295.73   268.8 2293.79   272.8 2293.86
   276.8 2294.95   280.8 2297.48   292.8 2311.02   307.9 2326.22   316.9 2333.33
   328.9 2344.53   336.9 2349.37   354.3 2365.91   356.9 2367.91   362.1 2369.64
#Mann= 3 ,-1,0
       0      .1       0  156.14    .045       0   173.1      .1       0
#XS Ineff= 2 , 0
                          194.37         2315.69
Permanent Ineff=
       F       F
Bank Sta=156.14,173.1
XS Rating Curve= 0 ,0
Exp/Cntr=0.3,0.1