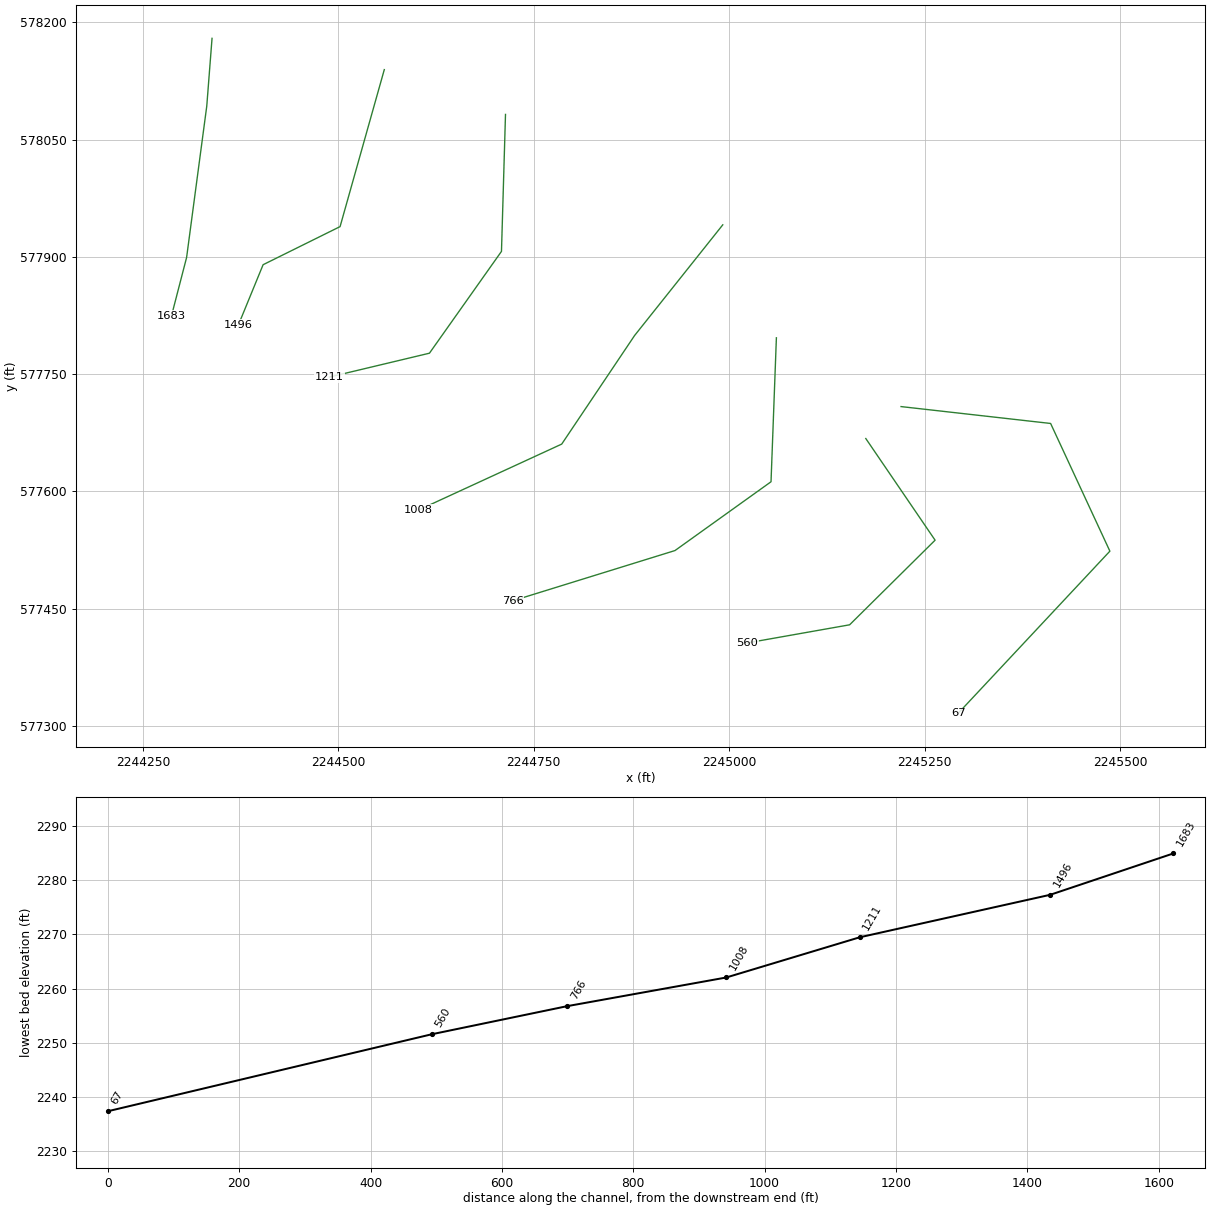
HEC-RAS study HAMILTRN.prj: HAMILTRN

--- HAMILTRN.g01 (geometry) --- (continued)

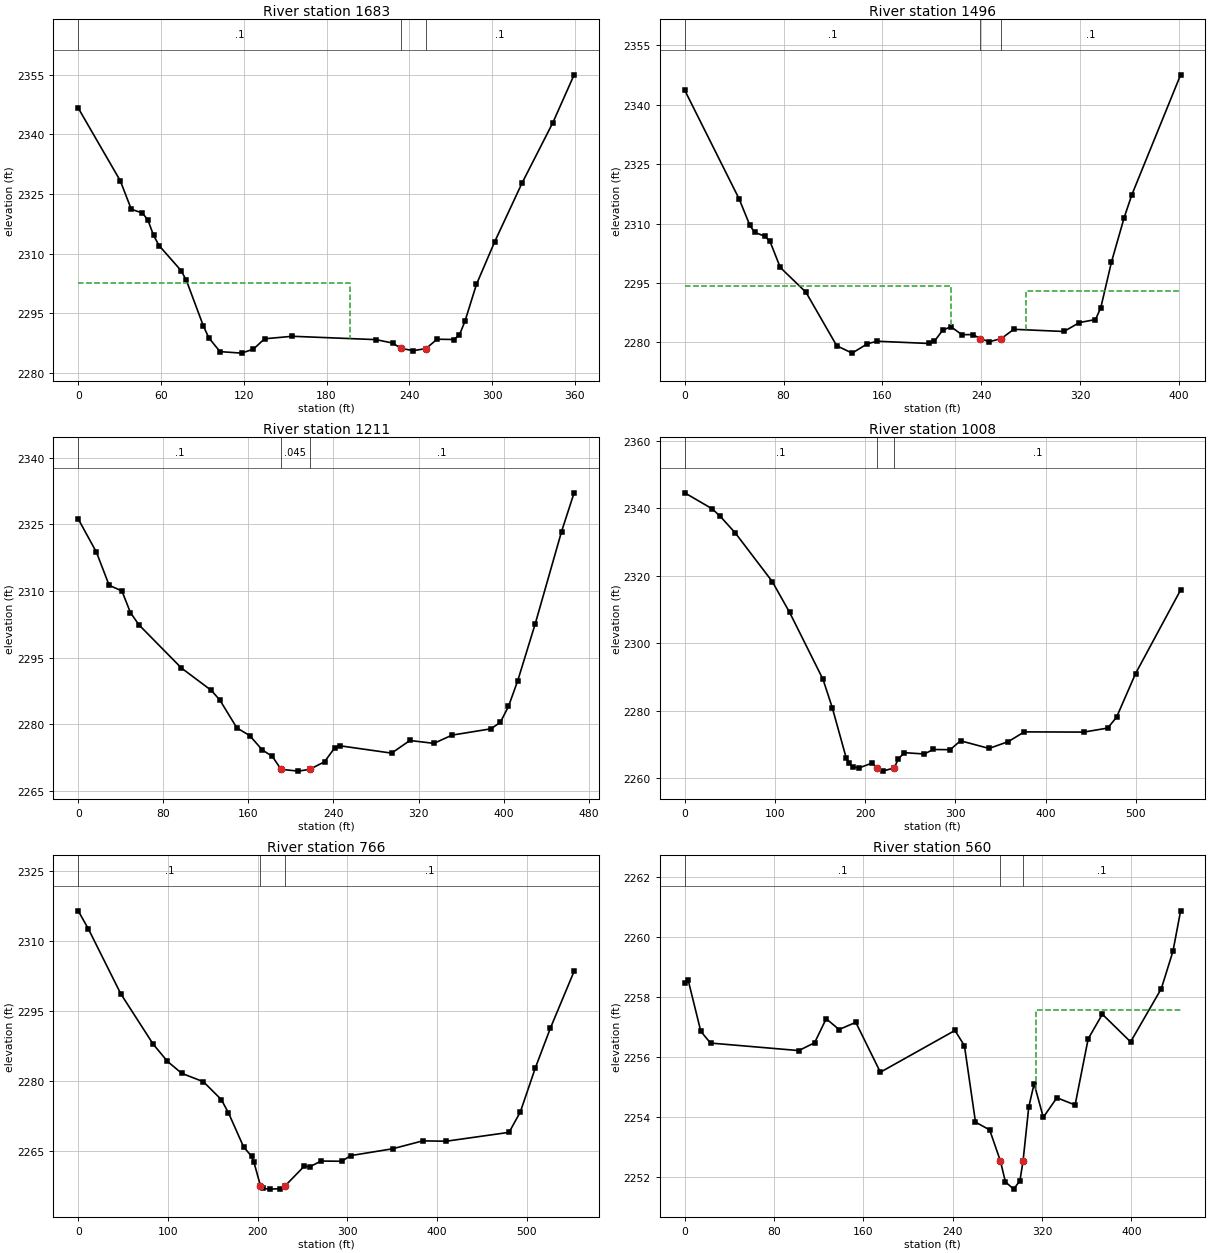
Type RM Length L Ch R = 1 ,1683    ,191.5,187.7,175
XS GIS Cut Line= 4
2244338.49106087578179.5896041632244331.74475838578092.853370956
2244305.96602782577899.326647509 2244286.5844012577824.488688529
#Sta/Elev= 30
       0 2346.63    30.5 2328.31    38.5 2321.13    46.6  2320.2    50.6 2318.36
    54.6 2314.59    58.6 2312.01    74.6  2305.7    78.4 2303.25    90.7  2291.8
    94.7 2288.77   102.8 2285.31   118.4 2284.93     127 2285.93   135.1 2288.54
   155.3 2289.17   215.8 2288.33   227.9 2287.47  234.08 2286.12     243 2285.55
   252.1 2286.08   260.2 2288.43   272.3 2288.36   276.3 2289.46   280.4 2292.97
   288.7 2302.23   301.9 2312.94   321.6 2327.63   344.1 2342.94   359.5 2354.98
#Mann= 3 ,-1,0
       0      .1       0  234.08    .045       0   252.1      .1       0
#XS Ineff= 2 , 0
          197.26 2302.48
Permanent Ineff=
       F       F
Bank Sta=234.08,252.1
XS Rating Curve= 0 ,0
Exp/Cntr=0.3,0.1

Type RM Length L Ch R = 1 ,1496    ,292,290,295.2
XS GIS Cut Line= 4
2244558.81899673578139.5760063152244502.26286959577938.782490358
2244403.80807653577890.0440881192244372.36348567 577813.37721929
#Sta/Elev= 30
       0 2343.63      44 2316.22    52.7 2309.55    56.5 2307.79    64.8 2306.78
      69 2305.48    77.3 2298.92    98.1 2292.66     123 2279.16   135.5  2277.3
   147.9 2279.68   155.8  2280.3   197.8 2279.73     202 2280.27   208.6 2283.04
   215.4 2283.97   224.3 2281.95   233.3 2281.98   239.3 2280.91   246.6 2280.18
  256.16 2280.97   266.3 2283.31   306.9 2282.76   319.4 2285.01   332.4 2285.77
   336.7 2288.77   345.3 2300.24   355.6 2311.47   361.8 2317.23   401.3 2347.51
#Mann= 3 ,-1,0
       0      .1       0   239.3    .045       0  256.16      .1       0
#XS Ineff= 2 , 0
          215.52 2294.28   276.5         2293.03
Permanent Ineff=
       F       F
Bank Sta=239.3,256.16
XS Rating Curve= 0 ,0
Exp/Cntr=0.3,0.1

Type RM Length L Ch R = 1 ,1211    ,202.5,203.2,203.2
XS GIS Cut Line= 4
2244713.83175387 578082.283874422244708.69617436577907.115584991
2244616.55685628577776.8681313522244488.64014218577746.346128147
#Sta/Elev= 30
       0 2326.24    17.1 2318.77    29.1  2311.3    41.1 2310.03    49.1 2305.16
    57.1  2302.4    97.1 2292.67   125.2 2287.64   133.2 2285.46   149.2  2279.2
   161.2 2277.48   173.2 2274.22   182.5 2272.79  190.762269.874     207 2269.47
  217.712269.876   231.6 2271.57   241.3 2274.75   245.9 2275.18   294.7 2273.52
   311.9 2276.37   334.4 2275.72   351.6 2277.58     388 2278.99   396.9 2280.44
   404.6 2284.04   413.3 2289.83   429.8 2302.68   454.5  2323.4   466.3 2332.12
#Mann= 3 ,-1,0
       0      .1       0  190.76    .045       0  217.71      .1       0
Bank Sta=190.76,217.71
XS Rating Curve= 0 ,0
Exp/Cntr=0.3,0.1

Type RM Length L Ch R = 1 ,1008    ,246.6,242.1,238.6
XS GIS Cut Line= 4
2244991.73759436577941.0549243832244878.98604532577799.524478567
2244785.74278785577660.613835757 2244602.7514389577576.335809948
#Sta/Elev= 30
       0 2344.53    30.5 2339.78    39.5 2337.52    56.1 2332.62      97 2318.25
   116.3 2309.07   153.3 2289.25   163.5 2280.91     179 2265.97   181.8 2264.53
     186 2263.31   193.2    2263   207.5 2264.43  213.312262.998   219.3 2262.06
  232.122262.999   236.8 2265.67   243.4 2267.53   265.7 2267.14   275.3 2268.47
   294.2 2268.41   305.7 2271.05   337.4 2268.78   358.8 2270.82   376.4 2273.69
   442.5 2273.63   468.9 2274.82   478.7 2278.05   499.7 2290.94   549.7 2315.74
#Mann= 3 ,-1,0
       0      .1       0  213.31    .045       0  232.12      .1       0
Bank Sta=213.31,232.12
XS Rating Curve= 0 ,0
Exp/Cntr=0.3,0.1

Type RM Length L Ch R = 1 ,766     ,204.1,205.8,208.2
XS GIS Cut Line= 4
2245060.32503753 577796.580507472245053.45475984 577612.44077669
 2244930.6383001577524.4526226892244722.96345652577460.127499405
#Sta/Elev= 30
       0 2316.43    11.4 2312.53    47.4 2298.66    83.5 2287.87    99.5 2284.16
   115.5 2281.59   139.5 2279.81   159.5 2275.98   167.5 2273.13   184.3 2265.86
   193.3  2263.8   195.7 2262.68  203.172257.498   205.5 2256.94   213.3 2256.78
   224.8 2256.87  230.752257.496   251.7 2261.64   258.6 2261.61   270.7  2262.8
   293.6 2262.75   303.9 2263.97   350.5 2265.43     384 2267.12   410.3 2267.05
   480.3 2268.95   492.9 2273.34   509.6 2282.77   526.4  2291.3   552.8 2303.47
#Mann= 3 ,-1,0
       0      .1       0  203.17    .045       0  230.75      .1       0
Bank Sta=203.17,230.75
XS Rating Curve= 0 ,0
Exp/Cntr(USF)=0,0
Exp/Cntr=0.3,0.1

Type RM Length L Ch R = 1 ,560     ,477.2,493.6,518.5
XS GIS Cut Line= 4
2245174.67159765577667.7261269492245263.30345904577537.716445093
2245153.98051718577429.4787125462245023.15130145577406.308868263
#Sta/Elev= 30
       0 2258.48     3.1 2258.56    14.4 2256.86    23.1 2256.47   102.1 2256.22
   116.3 2256.48   126.7 2257.28   138.2 2256.92   153.2 2257.16   175.2  2255.5
     242 2256.89   250.5 2256.38   260.4 2253.84   273.1 2253.58  282.75 2252.54
   287.2 2251.85   294.6 2251.61   300.2 2251.89  302.972252.542   308.1 2254.34
   312.9 2255.12   321.1    2254   333.3 2254.65   349.6 2254.41   361.3 2256.61
     374 2257.43   399.3 2256.51   426.8 2258.28   437.2 2259.52   444.1 2260.87
#Mann= 3 ,-1,0
       0      .1       0  282.75    .045       0  302.97      .1       0
#XS Ineff= 2 , 0
                          314.44         2257.57
Permanent Ineff=
       F       F
Bank Sta=282.75,302.97
XS Rating Curve= 0 ,0
Exp/Cntr(USF)=0,0
Exp/Cntr=0.3,0.1

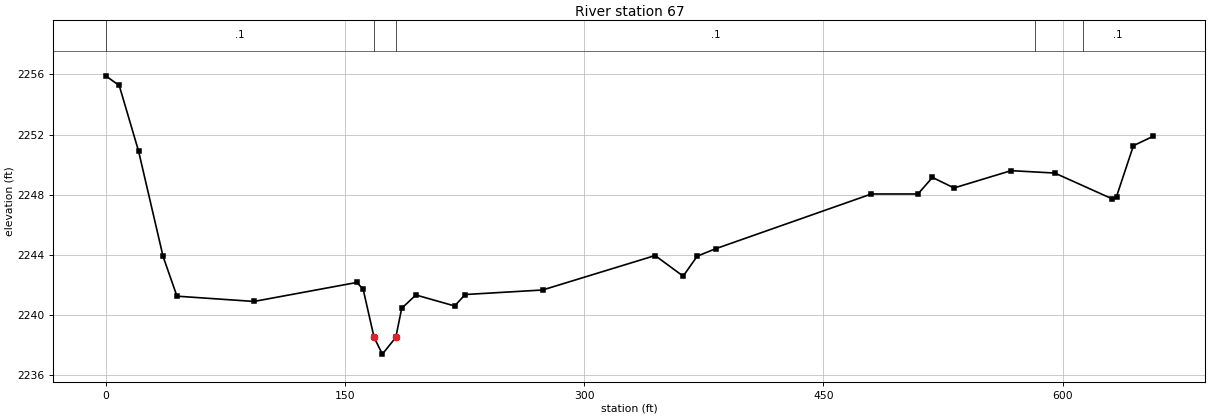
Type RM Length L Ch R = 1 ,67      ,,,
XS GIS Cut Line= 4
2245219.74321171577708.585913166 2245411.0632847577687.002777681
2245486.86009905577523.6624467322245292.72449696577316.191299818
#Sta/Elev= 30
       0  2255.9     8.5 2255.26    20.6 2250.91      36  2243.9    44.7 2241.26
      93 2240.91   157.4 2242.17   161.4 2241.74   168.32238.523   173.5 2237.41
  181.912238.522   185.6 2240.45   194.5 2241.34   218.8 2240.61   225.4 2241.37
   273.9 2241.67   344.5 2243.96   362.1 2242.59   370.9 2243.92   382.4 2244.41
   480.1 2248.05   509.3 2248.05   518.4 2249.15   531.9 2248.45   567.7  2249.6
   595.1 2249.44     631 2247.73   633.8 2247.88   644.4 2251.26   656.7 2251.88
#Mann= 5 ,-1,0
       0      .1       0   168.3    .045       0  181.91      .1       0
   582.6     .05       0   612.6      .1       0
Bank Sta=168.3,181.91
XS Rating Curve= 0 ,0
Exp/Cntr(USF)=0,0
Exp/Cntr=0.3,0.1
LCMann Table=0

Chan Stop Cuts=-1
Use User Specified Reach Order=0
Composite Channel Slope=5